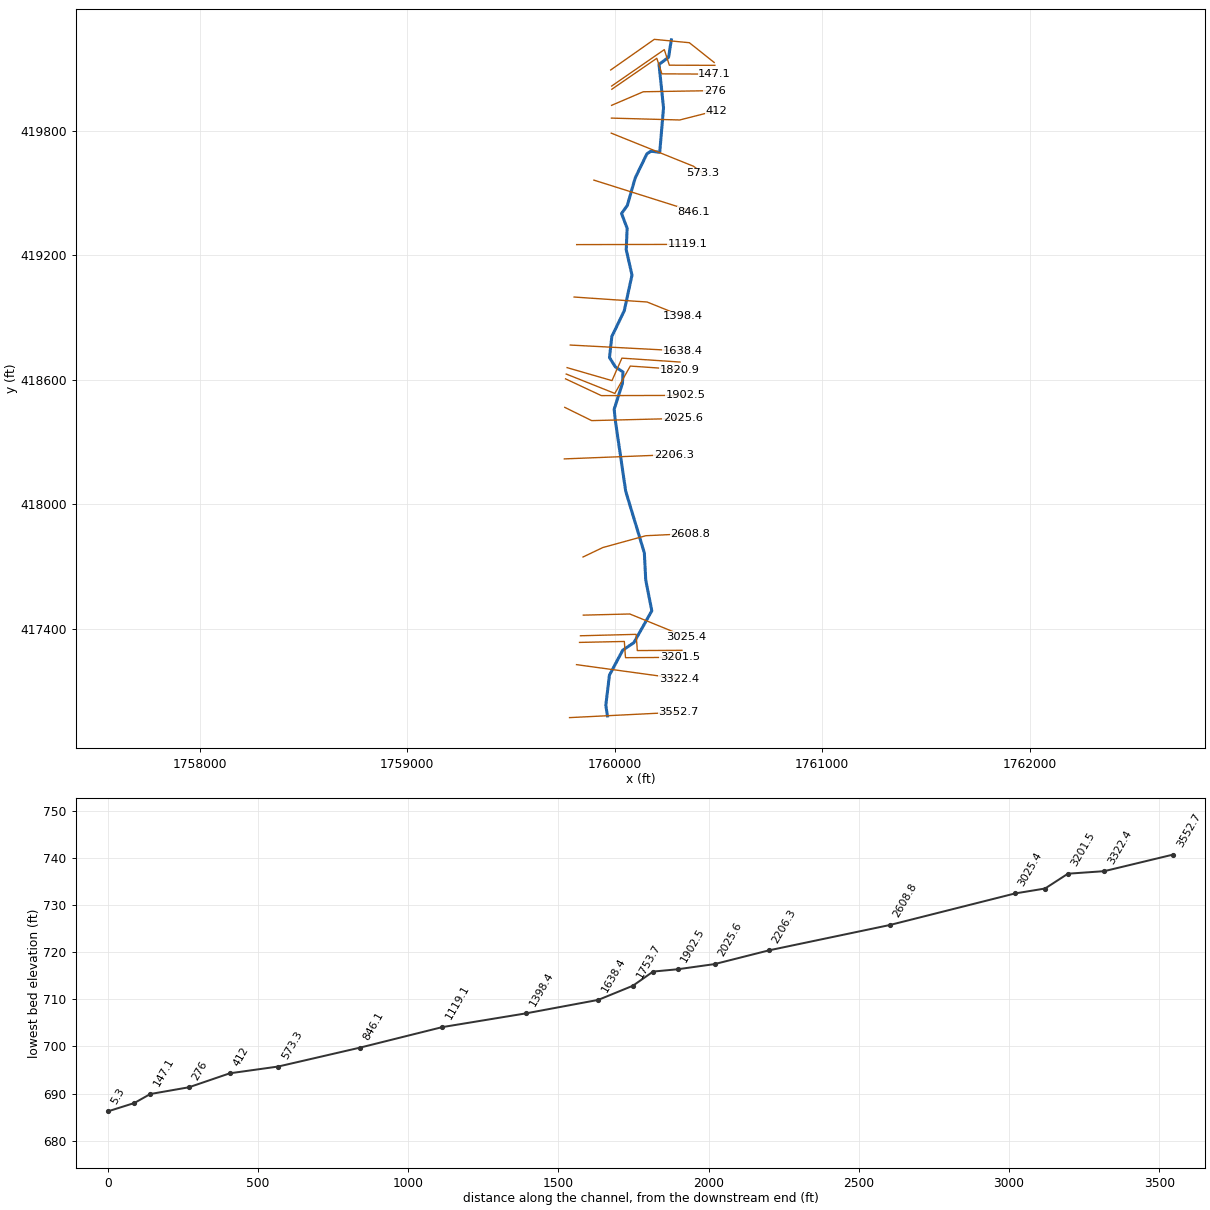
--- HONEYCMPFK.prj (project) ---

Proj Title=HONEYCMPFK
Current Plan=p01
Default Exp/Contr=0,0
English Units
Geom File=g01
Flow File=f01
Plan File=p01
BEGIN DESCRIPTION:
END DESCRIPTION:
DSS Export Rating Curves= 0
DSS Export Rating Curve Sorted= 0
DSS Export Volume Flow Curves= 0
DXF OffsetX= 0
DXF OffsetY= 0
DXF ScaleX= 0
DXF ScaleY= 0

--- HONEYCMPFK.p01 (plan) ---

Plan Title=Floodplain
Program Version=4.00
Geom File=g01
Flow File=f01
K Sum by GR=0
Std Step Tol=0.01
Critical Tol=0.01
Num of Std Step Trials=20
Max Error Tol=0.3
Flow Tol Ratio=0.001
Split Flow NTrial=30
Split Flow Tol=0.02
Split Flow Ratio=0.02
Log Output Level=0
Friction Slope Method=1
Unsteady Friction Slope Method=2
Unsteady Bridges Friction Slope Method=1
Global Log Level=0
CheckData=False
Run HTab=0
Run UNet=0
Run PostProcess=0
UNET Theta=0
UNET Theta Warmup=0
UNET ZTol=0
UNET ZSATol=0
UNET MxIter=0
UNET MaxInSteps=0
UNET DtIC=0
UNET DtMin=0
UNET MaxCRTS=0
UNET WFStab=0
UNET SFStab=0
UNET WFX=0
UNET SFX=0
UNET DSS MLevel=0
UNET DZMax Abort=0
UNET Convert EG Bridges=0
UNET Use Existing IB Tables=0
UNET Froude Limit=0
UNET Froude Power=0
Write IC File=0
Echo Input=False
Echo Output=False
Write Detailed=0

--- HONEYCMPFK.f01 (steady flow) ---

Flow Title=NFF Regression Equation
Program Version=4.00
Number of Profiles=1
Profile Names=P100yr
River Rch & RM=HONEYCMPFK,Main      ,3552.7
992.7234
River Rch & RM=HONEYCMPFK,Main      ,2608.8
1000.549
River Rch & RM=HONEYCMPFK,Main      ,573.3
1110.578
River Rch & RM=HONEYCMPFK,Main      ,276
1114.626
Boundary for River Rch & Prof#=HONEYCMPFK,Main      ,1
Up Type=0
Dn Type=3
Dn Slope=0.025723

--- HONEYCMPFK.g01 (geometry) ---

Geom Title=USGS 10m DEM
Program Version=4.10

River Reach=HONEYCMPFK      ,Main
Reach XY= 30
     1759965.452      416980.853     1759957.675      417032.381
     1759975.175      417177.241     1760039.341      417297.797
     1760092.813      417333.769     1760179.341      417487.381
     1760150.174      417635.353     1760143.369      417766.603
     1760053.543      418063.946     1760003.195      418406.828
     1759997.987      418458.912     1760037.918      418583.825
     1760040.522      418638.513     1760004.064      418662.818
     1759975.418      418707.957     1759986.702      418809.519
     1760046.598      418933.651     1760083.925      419105.439
     1760056.147      419227.835     1760060.487      419331.134
     1760033.578      419402.314     1760061.355      419441.377
      1760099.55      419574.103     1760155.973      419690.422
      1760175.07      419702.575     1760217.605      419697.366
     1760235.834      419911.776     1760214.133      420121.152
      1760260.14      420155.006     1760273.472      420239.189

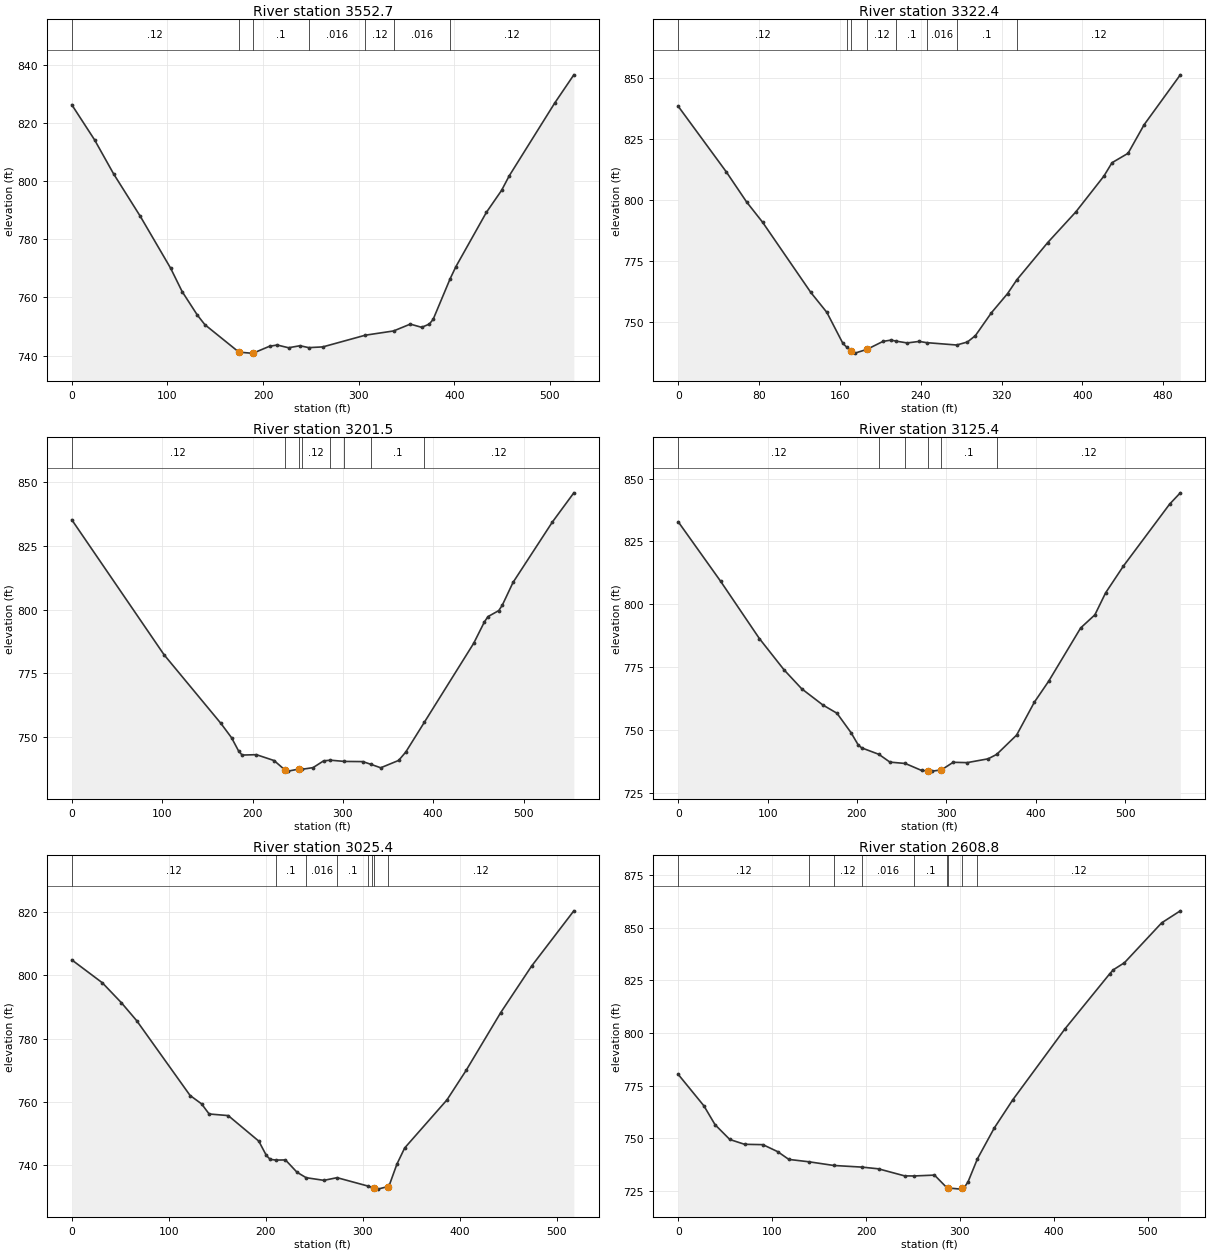
Type RM Length L Ch R = 1 ,3552.7  ,233.5,230.3,226.5
XS GIS Cut Line= 2
     1759782.895      416972.684     1760307.269       416998.74
#Sta/Elev= 30
       0  826.24    23.9  814.13    43.8  802.43    71.6   787.9   103.4  770.01
   115.4  761.99   131.3  753.91   139.2   750.6   174.8  741.16   186.9  740.82
   189.8  740.83   206.8  743.18   214.8  743.61   226.7  742.67   238.6  743.36
  247.79742.7124   262.5  742.96  306.94746.9845  336.51748.4447     354   750.8
   365.9  749.69   373.9  750.82   377.9  752.45  395.65766.4014   401.7  770.58
   433.5   789.2   449.4  796.77   457.4  801.77   505.1  826.87     525  836.52
#Mann= 7 ,-1 , 0
       0     .12       0   174.8    .045       0   189.8      .1       0
  247.79    .016       0  306.94     .12       0  336.51    .016       0
  395.65     .12       0
Bank Sta=174.8,189.8
XS Rating Curve= 0 ,0
Exp/Cntr=0.3,0.1

Type RM Length L Ch R = 1 ,3322.4  ,155.1,120.9,83.1
XS GIS Cut Line= 2
     1759816.484      417227.963     1760308.739      417160.476
#Sta/Elev= 30
       0  838.24    47.7  811.34    67.6  799.15    83.5  790.81   131.2  762.11
   147.1  753.94     163  741.22     167  739.64   170.9  738.26   174.9  737.28
   186.8  738.82   202.7  742.09   210.7  742.61   215.9742.1633   226.6  741.45
   238.5  742.07  245.71741.5708  275.53740.6011   286.2  741.83   294.1  744.44
     310  753.82   325.9  761.61  335.15767.2969   365.7  782.52   393.5  795.04
   421.3   809.7   429.3  815.16   445.2  819.02   461.1  830.71   496.9  851.11
#Mann= 8 ,-1 , 0
       0     .12       0     167    .045       0   170.9    .045       0
   186.8     .12       0   215.9      .1       0  245.71    .016       0
  275.53      .1       0  335.15     .12       0
Bank Sta=170.9,186.8
XS Rating Curve= 0 ,0
Exp/Cntr=0.3,0.1

Type RM Length L Ch R = 1 ,3201.5  ,57.4,76.1,72.3
XS GIS Cut Line= 4
     1759830.966      417335.121     1760046.958      417339.683
     1760052.601      417261.558     1760313.849      417263.147
#Sta/Elev= 30
       0  835.16   102.1  782.32     165  755.44   176.8  749.83   184.6  744.64
   188.5  743.03   204.3  743.18   223.9  740.88   235.6  737.28   239.5  736.74
   251.3  737.55   254.6  737.45     267  738.11   278.7  740.76  286.18741.0266
  301.69740.5388   322.1  740.47  331.23739.3793   341.9  738.05   361.7  740.93
   369.6  744.21   390.3755.9446   444.8  786.81   456.7  795.22   460.6  797.24
   472.5  799.59   476.4  801.69   488.3  810.62   531.9   834.3   555.6   845.7
#Mann= 8 ,-1 , 0
       0     .12       0   235.6    .045       0   251.3    .045       0
   254.6     .12       0  286.18      .1       0  301.69    .016       0
  331.23      .1       0   390.3     .12       0
Bank Sta=235.6,251.3
XS Rating Curve= 0 ,0
Exp/Cntr=0.3,0.1

Type RM Length L Ch R = 1 ,3125.4  ,90,100,136
XS GIS Cut Line= 4
     1759835.405      417367.146     1760103.816      417373.971
     1760109.458      417295.846      1760324.57      417297.024
#Sta/Elev= 30
       0  832.84    47.4  809.18    90.8  786.37   118.4  773.92   138.2  766.36
   161.9  759.91   177.7  756.62   193.5  748.85   201.4  744.02   205.3  742.85
  224.59740.2707   236.9  737.18  254.13736.6317   272.4  733.85   279.5  733.69
   284.2  733.59   294.5  734.07   307.7  737.11   323.3  736.97   346.8  738.49
  356.36740.2413   378.7  747.94   398.6  761.06   414.6   769.4   450.4   790.6
   466.3  795.81   478.3  804.56   498.2  815.21     550   839.9   561.9  844.37
#Mann= 6 ,-1 , 0
       0     .12       0  224.59    .016       0  254.13      .1       0
   279.5    .045       0   294.5      .1       0  356.36     .12       0
Bank Sta=279.5,294.5
XS Rating Curve= 0 ,0
Exp/Cntr=0.3,0.1

Type RM Length L Ch R = 1 ,3025.4  ,401.7,416.7,431.3
XS GIS Cut Line= 3
     1759849.188      417466.575     1760073.377      417472.164
     1760344.937      417361.383
#Sta/Elev= 30
       0  804.78    31.5  797.56    51.2  791.26    66.9  785.63     122  762.04
   133.8  759.41   141.6  756.22   161.3  755.71   192.8  747.67   200.6  743.15
   204.6  741.91   210.8741.6945   220.3  741.74   232.2  737.86  241.63736.1406
   259.9  735.31  273.53736.1481  305.42733.4996     309  733.18   311.4  732.86
   315.4  732.54  325.51  733.31   327.3  733.74   335.2  740.42   343.2  745.51
   386.8  760.66   406.6  769.98   442.2  788.16     474   802.8   517.6  820.23
#Mann= 8 ,-1 , 0
       0     .12       0   210.8      .1       0  241.63    .016       0
  273.53      .1       0  305.42     .12       0     309    .045       0
   311.4    .045       0  325.51     .12       0
Bank Sta=311.4,325.51
XS Rating Curve= 0 ,0
Exp/Cntr=0.3,0.1

Type RM Length L Ch R = 1 ,2608.8  ,407.4,402.4,397.1
XS GIS Cut Line= 4
     1759847.817      417746.785     1759943.352      417792.388
     1760150.458      417849.329     1760364.253      417859.462
#Sta/Elev= 30
       0   780.3    27.4  765.34    39.2  756.43    54.9   749.4    70.6  747.12
    90.2  746.94   105.9  743.62   117.8  739.94  139.74738.7803   165.5  737.07
  196.13 736.269   213.3  735.46   241.1  732.12  251.15732.0793   272.9  732.49
   285.8  726.63  287.07   726.4   300.8  725.83  302.57  726.21   304.7  726.62
   308.7  729.36  318.65  740.23   336.5   754.8   356.3  768.25   411.8  801.88
   459.4     828   463.3  829.95   475.2  833.32   514.9  852.27   534.7  857.96
#Mann= 9 ,-1 , 0
       0     .12       0  139.74     .06       0   165.5     .12       0
  196.13    .016       0  251.15      .1       0   285.8    .045       0
  287.07    .045       0  302.57      .1       0  318.65     .12       0
Bank Sta=287.07,302.57
XS Rating Curve= 0 ,0
Exp/Cntr=0.3,0.1

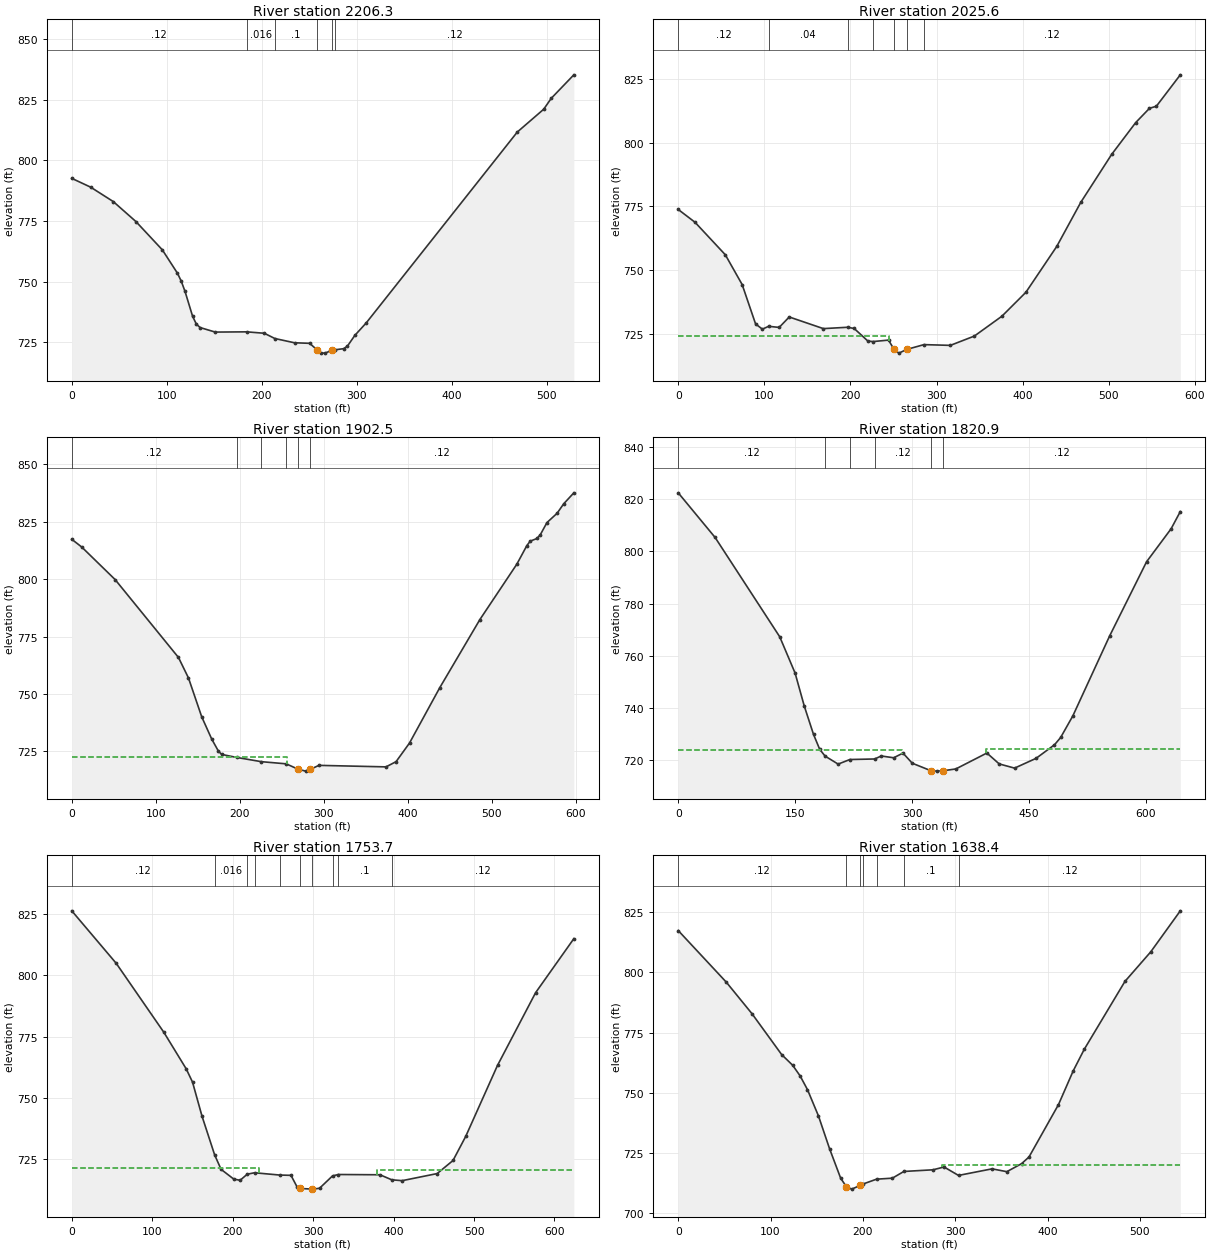
Type RM Length L Ch R = 1 ,2206.3  ,180.9,180.7,180
XS GIS Cut Line= 2
      1759757.83      418219.629     1760285.759      418240.354
#Sta/Elev= 30
       0  792.61    19.9  788.96    43.7  783.01    67.5  774.77    95.3  763.08
   111.2  753.44   115.2  750.16   119.2  745.89   127.1   735.7   131.1  732.41
   135.1  730.99     151  729.13   184.1 729.228   202.6  728.64  213.66726.4786
   234.4  724.71   250.3  724.49   258.2  721.76   262.2  720.52   266.2  720.44
   274.1  721.59   277.4  721.84     286  722.27     290  723.31   297.9  727.78
   309.8   732.9   468.8  811.73   496.6  821.15   504.5  825.64   528.3  835.35
#Mann= 6 ,-1 , 0
       0     .12       0   184.1    .016       0  213.66      .1       0
   258.2    .045       0   274.1    .045       0   277.4     .12       0
Bank Sta=258.2,274.1
XS Rating Curve= 0 ,0
Exp/Cntr=0.3,0.1

Type RM Length L Ch R = 1 ,2025.6  ,123,123.1,123.1
XS GIS Cut Line= 3
     1759759.934      418467.924     1759889.649      418404.142
     1760328.017      418414.993
#Sta/Elev= 30
       0  773.83    19.5  768.81    54.7  756.06    74.2  744.41    89.8  728.97
    97.7  726.91  104.94728.0352   117.2   727.6   128.9  731.69   168.5  727.13
   196.7 727.657   204.3  727.18   220.3  722.23  226.25722.0544   244.2  722.63
   250.6  718.98   256.2  717.52   265.6     719  285.34720.8545     316  720.56
   343.9  724.22   375.8  731.98   403.7  741.37   439.5  759.33   467.4  776.61
   503.3  795.43   531.2  807.89   547.2  813.49   555.2   814.3     583  826.61
#Mann= 7 ,-1 , 0
       0     .12       0  104.94     .04       0   196.7    .016       0
  226.25      .1       0   250.6    .045       0   265.6      .1       0
  285.34     .12       0
#XS Ineff= 2 , 0
          244.58  724.12
Permanent Ineff=
       F       F
Bank Sta=250.6,265.6
XS Rating Curve= 0 ,0
Exp/Cntr=0.3,0.1

Type RM Length L Ch R = 1 ,1902.5  ,11.5,81.6,121.4
XS GIS Cut Line= 3
     1759763.592      418605.383     1759936.059      418524.644
     1760343.208       418525.67
#Sta/Elev= 30
       0  817.34    11.9  813.95    51.6   799.8     127  765.89   138.9  756.98
   154.7  740.03   166.6  730.36   174.6  725.08   178.5  723.68  196.16722.3816
  225.69720.5389  255.23719.5912   268.8  717.36   278.2  716.42   283.8  717.18
   294.2  718.93     374  718.27     386  720.54     402  728.65   437.9  752.67
   485.8  782.42   529.7  806.48   541.7  814.61   545.7  816.53   553.7  817.68
   557.7  819.33   565.6  824.61   577.6  828.63   585.6  832.82   597.6  837.56
#Mann= 6 ,-1 , 0
       0     .12       0  196.16    .016       0  225.69      .1       0
  255.23     .12       0   268.8    .045       0   283.8     .12       0
#XS Ineff= 2 , 0
          256.35  722.47
Permanent Ineff=
       F       F
Bank Sta=268.8,283.8
XS Rating Curve= 0 ,0
Exp/Cntr=0.3,0.1

Type RM Length L Ch R = 1 ,1820.9  ,111.1,67.2,54
XS GIS Cut Line= 4
     1759766.833      418628.611     1760001.281      418535.088
     1760075.586      418667.032     1760315.169      418650.366
#Sta/Elev= 30
       0  822.35    47.3  805.28   130.2  767.29   149.9  753.42   161.7  740.78
   173.5     730   181.4  724.31  188.36721.6734   205.1  718.62  220.16720.3678
  251.96720.5749   260.4  721.72   276.3  721.04   288.3  722.82   300.2  718.95
   324.2  716.08   332.1  715.93   339.2  716.05     356  716.76   395.9  722.85
   411.7  718.69   431.4  717.08     459  720.82   482.6     726   490.5  728.79
   506.2  737.08   553.4  767.66   600.7  795.98   632.2  808.61     644  815.19
#Mann= 6 ,-1 , 0
       0     .12       0  188.36    .016       0  220.16      .1       0
  251.96     .12       0   324.2    .045       0   339.2     .12       0
#XS Ineff= 2 , 0
          286.79  723.89  395.15          724.36
Permanent Ineff=
       F       F
Bank Sta=324.2,339.2
XS Rating Curve= 0 ,0
Exp/Cntr=0.3,0.1

Type RM Length L Ch R = 1 ,1753.7  ,143.2,115.3,87.4
XS GIS Cut Line= 4
     1759771.128      418659.397     1759987.392      418596.894
     1760035.308      418705.227     1760315.169      418686.477
#Sta/Elev= 30
       0  826.33    55.3  804.92   114.5  776.81   142.2  761.96   150.1  756.53
   161.9  742.64  177.64726.8395   185.6  720.98   201.4     717   209.3  716.53
  218.13719.0074  227.23  719.59  258.41718.6576   272.5  718.54   280.4   713.6
   283.8  713.18   298.8  712.94   300.1  712.92     308  713.28  324.12718.3064
  331.42718.8771   383.1  718.77  397.85716.7097   410.7  716.37   454.2  719.26
   473.9  724.59   489.7  734.41   529.2  763.34   576.6  792.99   624.1  814.99
#Mann= 10 ,-1 , 0
       0     .12       0  177.64    .016       0  218.13      .1       0
  227.23    .016       0  258.41      .1       0   283.8    .045       0
   298.8      .1       0  324.12    .016       0  331.42      .1       0
  397.85     .12       0
#XS Ineff= 2 , 0
          233.33  721.52  379.26          720.57
Permanent Ineff=
       F       F
Bank Sta=283.8,298.8
XS Rating Curve= 0 ,0
Exp/Cntr=0.3,0.1

Type RM Length L Ch R = 1 ,1638.4  ,240.2,240,239.6
XS GIS Cut Line= 2
     1759786.328      418768.329      1760329.38      418739.813
#Sta/Elev= 30
       0  817.37      52  795.95      80  782.76     112  765.84     124  761.36
     132  756.97     140  751.25   151.9  740.31   163.9  726.71   175.9  714.48
  182.09   710.9   187.9  709.91  197.33  711.49   200.6   712.1  214.83714.0518
   231.9  714.46   244.4717.2563   275.9  717.94   287.9  719.11  303.56715.6059
   339.9  718.34   355.9  717.16   371.9   720.5   379.9  723.26   411.8     745
   427.8  759.06   439.8  768.05   483.8  796.22   511.8  808.53   543.8  825.57
#Mann= 7 ,-1 , 0
       0     .12       0  182.09    .045       0  197.33    .045       0
   200.6     .12       0  214.83    .016       0   244.4      .1       0
  303.56     .12       0
#XS Ineff= 2 , 0
                          286.07           720.1
Permanent Ineff=
       F       F
Bank Sta=182.09,197.33
XS Rating Curve= 0 ,0
Exp/Cntr=0.3,0.1

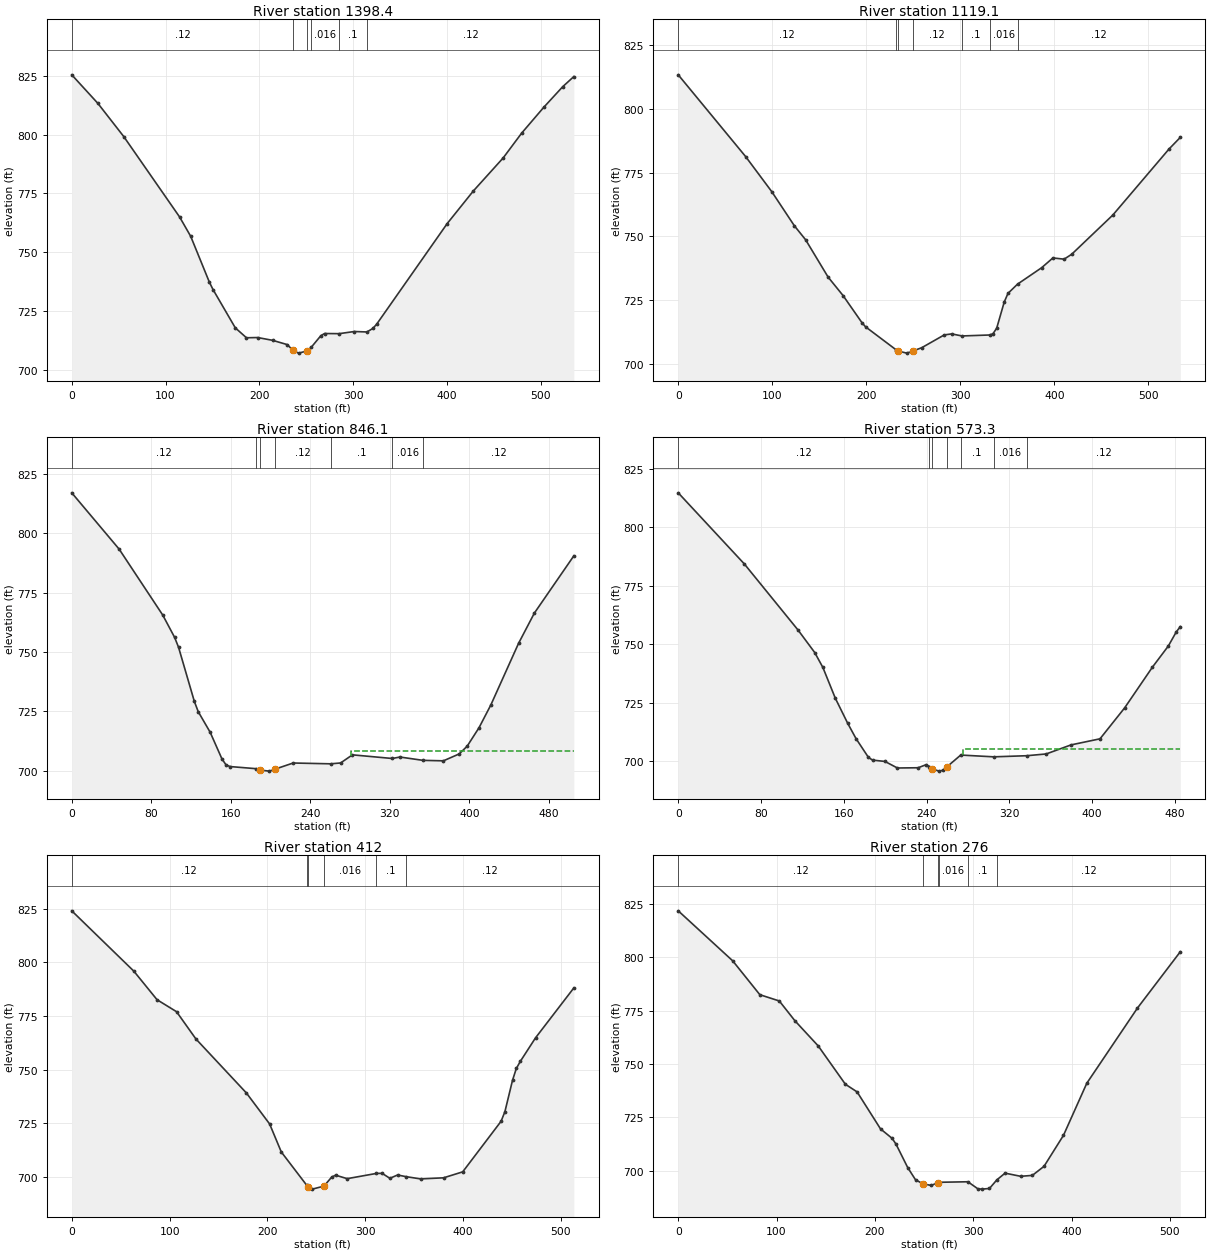
Type RM Length L Ch R = 1 ,1398.4  ,277.3,279.2,280.5
XS GIS Cut Line= 3
     1759804.971      418999.736     1760156.966      418975.713
     1760326.237      418907.354
#Sta/Elev= 30
       0  825.41    27.8  813.29    55.5  799.12     115  764.95   126.8  756.75
   146.7  737.26   150.6  734.11   174.4  717.79   186.3  713.58   198.2  713.68
   214.1   712.5   229.9  710.66   235.9  708.19   241.8  707.05   250.9  707.96
  255.55709.6225   265.6  714.46   269.6  715.39  285.16715.3294   301.3  716.24
  314.76 716.054   321.1  717.56   325.1  719.34   400.4  762.18   428.2     776
     460  790.05   479.8  800.64   503.6  811.72   523.5  820.35   535.4  824.67
#Mann= 6 ,-1 , 0
       0     .12       0   235.9    .045       0   250.9     .12       0
  255.55    .016       0  285.16      .1       0  314.76     .12       0
Bank Sta=235.9,250.9
XS Rating Curve= 0 ,0
Exp/Cntr=0.3,0.1

Type RM Length L Ch R = 1 ,1119.1  ,279.7,273,264.8
XS GIS Cut Line= 2
     1759817.214       419252.44     1760351.194      419253.491
#Sta/Elev= 30
       0  813.41    71.7   781.3    99.6  767.47   123.5  754.14   135.5  748.63
   159.4  733.98   175.3  726.73   195.3  716.13   199.2  714.46   231.5  705.48
   233.4  704.98   243.1  704.12  249.22  704.91     259  706.25   282.9  711.27
   290.9  711.67  301.79 710.864  331.33711.2433   334.7  711.71   338.7   713.9
   346.7  724.16   350.7  727.58  360.86731.2063   386.5  737.66   398.5   741.5
   410.4  741.02   418.4  742.92   462.2  758.34     522  784.28     534  788.85
#Mann= 7 ,-1 , 0
       0     .12       0   231.5    .045       0   233.4    .045       0
  249.22     .12       0  301.79      .1       0  331.33    .016       0
  360.86     .12       0
Bank Sta=233.4,249.22
XS Rating Curve= 0 ,0
Exp/Cntr=0.3,0.1

Type RM Length L Ch R = 1 ,846.1   ,233.3,272.8,267.9
XS GIS Cut Line= 2
     1759900.222      419563.248     1760381.811      419411.168
#Sta/Elev= 30
       0  817.02    47.7  793.27    91.5  765.52   103.4  756.16   107.4  751.96
   123.3  729.12   127.2  724.81   139.2  716.15   151.1  704.87   155.1  702.45
   159.1   701.7   185.4   700.8  188.85  700.21   198.8  699.77  204.71  700.64
   222.7  703.19  260.41702.8482   270.4  703.21   282.3  706.63  322.35705.0969
   330.1  705.71  353.33704.3057   373.8  704.11   389.7  707.02   397.7  710.28
   409.6  718.04   421.5  727.64   449.4  753.61   465.3  766.36     505  790.48
#Mann= 7 ,-1 , 0
       0     .12       0   185.4    .045       0  188.85    .045       0
  204.71     .12       0  260.41      .1       0  322.35    .016       0
  353.33     .12       0
#XS Ineff= 2 , 0
                           280.5          708.38
Permanent Ineff=
       F       F
Bank Sta=188.85,204.71
XS Rating Curve= 0 ,0
Exp/Cntr=0.3,0.1

Type RM Length L Ch R = 1 ,573.3   ,189.9,161.3,169.1
XS GIS Cut Line= 3
     1759983.887       419789.67     1760380.491       419630.01
     1760426.753      419595.644
#Sta/Elev= 30
       0  814.67    63.9  784.27   115.9  755.97   131.9  746.42   139.8  740.03
   151.8  726.89   163.8  716.15   171.8  709.65   183.8  701.62   187.8  700.45
   199.8  699.88   211.8  697.08   231.8  697.18   239.7  698.52   242.8  697.69
  245.49  696.84   251.7  695.74   255.7  696.08   259.7  697.59  273.01702.6099
  304.85701.8483  336.69702.3209   355.6  703.08   379.6  706.95   407.6  709.55
   431.4  722.77   458.3  740.21   473.6  749.19   481.3  755.24   485.2   757.5
#Mann= 7 ,-1 , 0
       0     .12       0   242.8    .045       0  245.49    .045       0
   259.7     .12       0  273.01      .1       0  304.85    .016       0
  336.69     .12       0
#XS Ineff= 2 , 0
                          275.03          705.07
Permanent Ineff=
       F       F
Bank Sta=245.49,259.7
XS Rating Curve= 0 ,0
Exp/Cntr=0.3,0.1

Type RM Length L Ch R = 1 ,412     ,134.9,135.9,136.9
XS GIS Cut Line= 3
     1759984.805      419862.149     1760313.867        419853.1
     1760492.309      419898.434
#Sta/Elev= 30
       0  824.02    63.5  795.88    87.2  782.58   107.1  777.01   126.9  764.31
   178.5  739.14   202.3  724.66   214.2  711.63   240.1  696.16   241.9  695.18
   245.9   694.3   257.8   695.7   265.7  699.89   269.7   700.8   281.6  699.18
  311.54701.6252   317.3  701.66   325.2  699.35   333.1  700.89  341.46 700.139
   356.6  699.06   380.1  699.57   399.7  702.36   438.9  725.92   442.8  730.37
   450.6  745.02   454.5  750.54   458.5  753.79   474.1   764.8   513.3  788.09
#Mann= 6 ,-1 , 0
       0     .12       0   240.1    .045       0   241.9    .045       0
   257.8    .016       0  311.54      .1       0  341.46     .12       0
Bank Sta=241.9,257.8
XS Rating Curve= 0 ,0
Exp/Cntr=0.3,0.1

Type RM Length L Ch R = 1 ,276     ,162,128.9,86.7
XS GIS Cut Line= 3
     1759985.584      419923.678     1760138.229      419989.097
     1760482.673      419994.653
#Sta/Elev= 30
       0  821.72    55.4  798.29      83  782.42   102.8  779.48   118.6  770.25
   142.4   758.4     170  740.46   181.9  736.88   205.7  719.56   217.6  715.08
   221.5  712.39   233.4  701.41   241.3  695.72   248.7  693.86   257.2  693.05
   263.7  694.27  265.01 694.532  294.55694.7792   304.7  691.49   308.6  691.33
   316.5  691.63  324.09695.6973   332.4  698.82   348.2  697.34   360.1  697.76
     372  702.01   391.8  716.55   415.5  740.94     467  776.16   510.6  802.55
#Mann= 6 ,-1 , 0
       0     .12       0   248.7    .045       0   263.7     .12       0
  265.01    .016       0  294.55      .1       0  324.09     .12       0
Bank Sta=248.7,263.7
XS Rating Curve= 0 ,0
Exp/Cntr=0.3,0.1

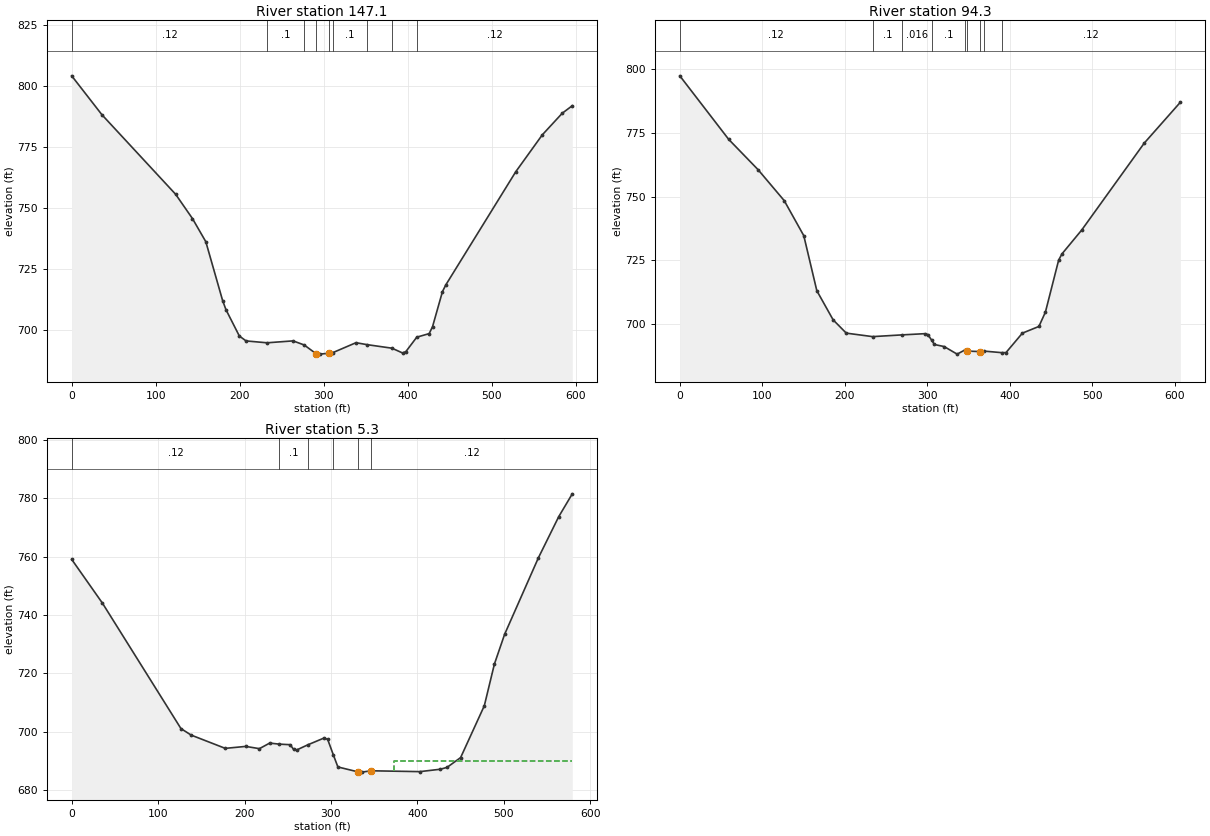
Type RM Length L Ch R = 1 ,147.1   ,54.6,52.9,64.6
XS GIS Cut Line= 4
     1759986.564      420001.128     1760203.507      420150.469
     1760227.812      420075.469     1760481.285       420074.08
#Sta/Elev= 30
       0  804.19    35.9  788.24   123.7  755.54   143.7  745.57   159.6  736.06
   179.6  711.89   183.6  708.13   199.5  697.33   207.5  695.31  232.51694.5433
   263.4  695.33  276.71693.6431   291.2  689.96   294.9  689.89   306.2  690.25
  311.02690.5399   338.3  694.58  351.56693.7797  381.09692.3292   393.7  690.37
   397.7  690.94  410.63696.8501   425.4  698.32   429.4  701.16   441.2  715.57
   445.2  718.33   528.4  764.78     560  779.94   583.8  788.84   595.7  791.92
#Mann= 9 ,-1 , 0
       0     .12       0  232.51      .1       0  276.71    .016       0
   291.2    .045       0   306.2    .016       0  311.02      .1       0
  351.56    .016       0  381.09      .1       0  410.63     .12       0
Bank Sta=291.2,306.2
XS Rating Curve= 0 ,0
Exp/Cntr=0.3,0.1

Type RM Length L Ch R = 1 ,94.3    ,57.1,88.9,115.9
XS GIS Cut Line= 4
     1759985.845      420016.625     1760239.618      420192.136
     1760263.923      420117.136     1760483.368      420116.441
#Sta/Elev= 30
       0  797.48    59.3  772.47    94.9  760.55   126.6  748.37   150.3  734.58
   166.1  712.93   185.9  701.45   201.8  696.24  233.73694.8666  269.64695.5544
   296.7  696.02   300.6   695.7  305.56693.3508   308.6  691.77   320.4  690.96
   336.2  687.98   345.4  689.58     348  689.19   363.7  688.98  368.95689.1673
  390.16688.5612   395.4  688.58   415.3  696.24   435.3  698.87   443.2  704.52
   459.2  724.93   463.2   727.4   487.1  736.77     563  771.01   606.8  787.09
#Mann= 9 ,-1 , 0
       0     .12       0  233.73      .1       0  269.64    .016       0
  305.56      .1       0   345.4    .045       0     348    .045       0
   363.7      .1       0  368.95    .016       0  390.16     .12       0
Bank Sta=348,363.7
XS Rating Curve= 0 ,0
Exp/Cntr=0.3,0.1

Type RM Length L Ch R = 1 ,5.3     ,4.6,5.3,6.1
XS GIS Cut Line= 4
     1759981.424      420094.175     1760191.493      420241.745
     1760360.451      420225.469     1760479.896       420130.33
#Sta/Elev= 30
       0  759.06    35.6  744.06   126.4  701.11   138.2  698.88   177.7  694.33
   201.4     695   217.2  694.23   229.1  696.14  240.33695.7715   252.8  695.59
   256.7  693.99   260.7  693.83  272.92695.5052   292.2   697.9   296.2  697.38
  302.59692.2129     308  687.96   331.5  686.26   335.7  686.19   346.5  686.65
   402.8  686.36   426.5  687.18   434.3  687.82     450  691.17   477.4  708.91
   489.1  723.22   500.9  733.39     540  759.61   563.5  773.69   579.2  781.52
#Mann= 6 ,-1 , 0
       0     .12       0  240.33      .1       0  272.92    .016       0
  302.59      .1       0   331.5    .045       0   346.5     .12       0
#XS Ineff= 2 , 0
                          373.37          689.93
Permanent Ineff=
       F       F
Bank Sta=331.5,346.5
XS Rating Curve= 0 ,0
Exp/Cntr=0.3,0.1

Chan Stop Cuts=-1
Use User Specified Reach Order=0
Composite Channel Slope=5